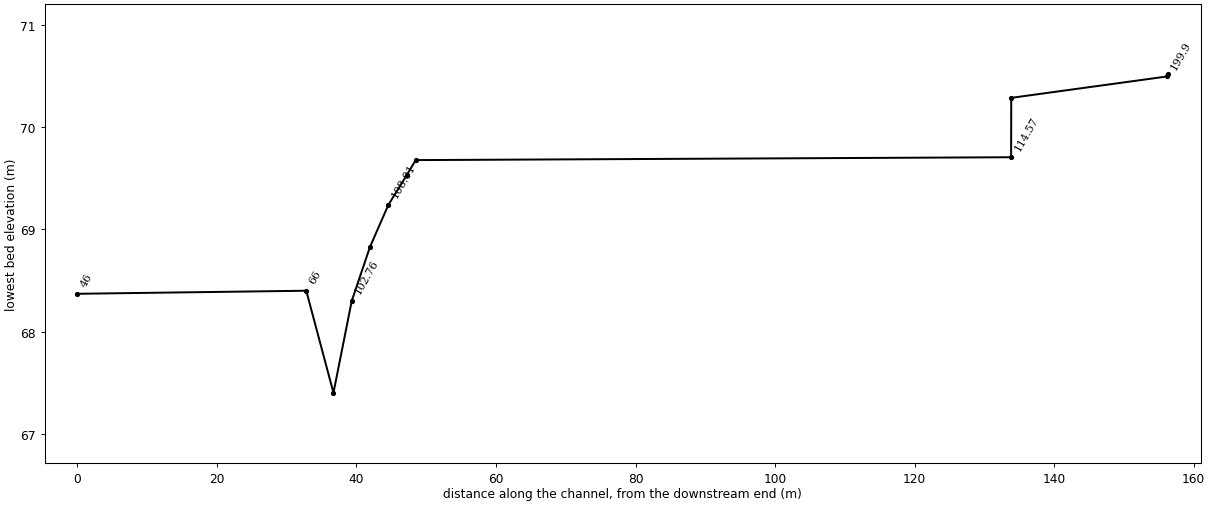
--- HECRAS_v0_EstructuraRapidaCauceLateral.prj (project) ---

Proj Title=HECRAS_v0_EstructuraRapidaCauceLateral
Current Plan=p01
Default Exp/Contr=0.3,0.1
SI Units
Geom File=g01
Flow File=f01
Unsteady File=u01
Plan File=p01
Y Axis Title=Elevation
X Axis Title(PF)=Main Channel Distance
X Axis Title(XS)=Station
BEGIN DESCRIPTION:
END DESCRIPTION:
DSS Export Rating Curves= 0
DSS Export Rating Curve Sorted= 0
DSS Export Volume Flow Curves= 0
DXF OffsetX= 0
DXF OffsetY= 0
DXF ScaleX= 1
DXF ScaleY= 10

--- HECRAS_v0_EstructuraRapidaCauceLateral.p01 (plan) ---

Plan Title=Plan 01
Program Version=6.70
Short Identifier=FNP_CL1
Simulation Date=01SEP2008,00:15,02SEP2008,00:15
Geom File=g01
Flow File=u01
Subcritical Flow
K Sum by GR= 0
Std Step Tol= 0.003
Critical Tol= 0.003
Num of Std Step Trials= 20
Max Error Tol= 0.1
Flow Tol Ratio= 0.001
Split Flow NTrial= 30
Split Flow Tol= 0.006
Split Flow Ratio= 0.02
Log Output Level= 0
Friction Slope Method= 1
Unsteady Friction Slope Method= 2
Unsteady Bridges Friction Slope Method= 1
Parabolic Critical Depth
Global Vel Dist= 0 , 0 , 0
Global Log Level= 0
CheckData=True
Encroach Param=-1 ,0,0, 0
Flow Ratio Tolerance=0.1
Flow Ratio Min Ratio=0.5
Flow Ratio Max Ratio=4
Flow Ratio Max Iterations= 10
Computation Interval=1MIN
Output Interval=1MIN
Instantaneous Interval=1MIN
Mapping Interval=1MIN
Computation Time Step Use Courant=        0
Computation Time Step Use Time Series=    0
Computation Time Step Count To Double=0
Computation Time Step Max Doubling=0
Computation Time Step Max Halving=0
Computation Time Step Residence Courant=0
Run HTab=-1
Run UNet=-1
Run Sediment= 0
Run PostProcess=-1
Run WQNet= 0
Run RASMapper= 0
UNET Theta= 1
UNET Theta Warmup= 1
UNET ZTol= 0.006
UNET ZSATol= 0.006
UNET MxIter= 20
UNET Max Iter WO Improvement= 0
UNET MaxInSteps= 0
UNET DtIC= 0
UNET DtMin= 0
UNET MaxCRTS= 20
UNET WFStab= 2
UNET SFStab= 1
UNET WFX= 1
UNET SFX= 1
UNET Gravity=9.80665
UNET 1D Methodology=Finite Difference
UNET DSS MLevel= 4
UNET Pardiso=0
UNET DZMax Abort= 30
UNET Use Existing IB Tables=-1
UNET Froude Reduction=False
UNET Froude Limit= 0.8
UNET Froude Power= 4
UNET D1 Cores= 0
UNET WindReference=Eulerian
UNET WindDragFormulation=Hsu (1988)
UNET D2 Coriolis=0
UNET D2 Cores= 0
UNET D2 Theta= 1
UNET D2 Theta Warmup= 1
UNET D2 Z Tol= 0.003
UNET D2 Volume Tol= 0.003
UNET D2 Max Iterations= 20
UNET D2 Advanced Convergence=0
UNET D2 WS Max Tol=0.045
UNET D2 WS RMS Tol=0.006
UNET D2 WS Stall Tol=1
UNET D2 Equation= 0
UNET D2 RampUpFraction=0.1
UNET D2 TimeSlices= 1
UNET D2 Turbulence Formulation=None
UNET D2 Eddy Viscosity=0.3
UNET D2 Transverse Eddy Viscosity=0.1
UNET D2 Smagorinsky Mixing=0.05
UNET D2 BCVolumeCheck=0
UNET D2 Cores=0
UNET D2 SolverType=PARDISO (Direct)
UNET D2 Minimum Iterations= 3
UNET D2 Maximum Iterations= 30
UNET D2 Restart Number= 10
UNET D2 Relaxation Coeff=1.3
UNET D2 SOR Precondition Iterations= 10
UNET D2 ILUT Maximum Fill= 8
UNET D2 ILUT Tolerance=1E-08
UNET D2 Convergence Tolerance=0.00001
Secondary Flow Approach=None
Spiral Intensity Factor=1
Spiral Intensity Adaptation Factor=1
Spiral Intensity Diffusion Factor=1
Momentum Dispersion Factor=1
Flow Smoothing Iterations=10
PS Theta= 1
PS WS Tol= 0.003
PS Volume Tol= 0.003
PS Max Iterations= 20
PS Equation= 0
PS Advance Time Step=-1
PS Target Courant=0.9
PS Time Slices= 1
PS Iterate With 2D=0
PS Project Initial WSE from DS=-1
PS Ramp Up Initial WSE from US=-1
PS Cores=0
UNET D1D2 MaxIter= 0
UNET D1D2 ZTol=0.003
UNET D1D2 QTol=0.1
UNET D1D2 MinQTol=0.03
DSS File=dss
Write IC File= 0
Write IC File at Fixed DateTime=0
Write IC File at Sim End=0
Echo Input=False
Echo Parameters=False
Echo Output=False
Write Detailed= 0
HDF Write Warmup=0
HDF Write Time Slices=0
HDF Flush=0
HDF Compression= 1
HDF Chunk Size= 1
HDF Spatial Parts= 1
HDF Use Max Rows=0
HDF Fixed Rows= 1
Calibration Method= 0
Calibration Iterations= 20
Calibration Max Change=0.05
Calibration Tolerance=0.2
Calibration Maximum=1.5
Calibration Minimum=0.5
Calibration Optimization Method= 1
WQ AD Non Conservative
WQ ULTIMATE=-1
WQ Max Comp Step=1HOUR
WQ Output Interval=15MIN
WQ Output Selected Increments= 0
WQ Create Restart=0
WQ Fixed Restart=0
WQ System Summary=0
WQ Write To DSS=0
Sorting and Armoring Iterations= 10
XS Update Threshold= 0.02
Bed Roughness Predictor= 0
Processes Affected by Predictor=Sediment Only
Hydraulics Update Threshold= 0.02
Energy Slope Method= 1
Volume Change Method= 1
Sediment Retention Method= 0
Sediment TS Multiplier= 1
Warm Up Method= 0
XS Weighting Method= 0
Number of US Weighted Cross Sections= 1
Number of DS Weighted Cross Sections= 1
Upstream XS Weight=0
Main XS Weight=1
Downstream XS Weight=0
Number of DS XS's Weighted with US Boundary= 1
Upstream Boundary Weight= 1
Weight of XSs Associated with US Boundary= 0
Number of US XS's Weighted with DS Boundary= 1
Downstream Boundary Weight= 0.5
Weight of XSs Associated with DS Boundary= 0.5
Percentile Method= 0
Sediment Output Level= 3
Mass or Volume Output= 0
Output Increment Type= 1
Profile and TS Output Increment= 1
Transport Output Increment 1
XS Output Flag= 0
XS Output Increment= 10
Read HDF5 Sediment Hotstart= 0
Sediment Hotstart Type= 0
Write Gradation File= 0
Read Gradation Hotstart= 0
Write HDF5 File= 1
Write Binary Output= 1
Write DSS Sediment File= 0
DSS Sediment Output Type= 1
SV Curve= 0
Specific Gage Flag= 0
Subcell Erosion Methods= 0
Subcell Deposition Methods= 0
Advection Scheme= 1
Matrix Solver= 0
Implicit Weighting Factor= 1
Maximum Outer Loop Convergence Iterations= 5
Convergence Maximum Absolute= 0.001
Convergence RMSE= 0.0001
Grain Fractions Max Abs Error= 0.001
Max Subgrid Regions= 1
Max Subgrid Length Scale= 3.402823E+38
Initial Layer Thickness= 3
Min Layer Thickness= 0.1
Max Layer Thickness= 6
Number of Layers= 5

--- HECRAS_v0_EstructuraRapidaCauceLateral.f01 (steady flow) ---

Flow Title=FP
Program Version=6.70
Number of Profiles= 7
Profile Names=Qtr2.33,Qtr5,Qtr10,Qtr25,Qtr50,Qtr100,Qm
River Rch & RM=CauceLat1,CauceLat1       ,200
      42    59.5    74.2    93.3   107.7   122.2     .11
Boundary for River Rch & Prof#=CauceLat1,CauceLat1       , 1
Up Type= 0
Dn Type= 3
Dn Slope=0.009287
Boundary for River Rch & Prof#=CauceLat1,CauceLat1       , 2
Up Type= 0
Dn Type= 3
Dn Slope=0.009287
Boundary for River Rch & Prof#=CauceLat1,CauceLat1       , 3
Up Type= 0
Dn Type= 3
Dn Slope=0.009287
Boundary for River Rch & Prof#=CauceLat1,CauceLat1       , 4
Up Type= 0
Dn Type= 3
Dn Slope=0.009287
Boundary for River Rch & Prof#=CauceLat1,CauceLat1       , 5
Up Type= 0
Dn Type= 3
Dn Slope=0.009287
Boundary for River Rch & Prof#=CauceLat1,CauceLat1       , 6
Up Type= 0
Dn Type= 3
Dn Slope=0.009287
Boundary for River Rch & Prof#=CauceLat1,CauceLat1       , 7
Up Type= 0
Dn Type= 3
Dn Slope=0.009287
DSS Import GetInterval= 0
DSS Import GetPeak= 0
DSS Import FillOption= 0

--- HECRAS_v0_EstructuraRapidaCauceLateral.u01 (unsteady flow) ---

Flow Title=FNP
Program Version=6.70
Use Restart= 0
Initial Flow Loc=CauceLat1       ,CauceLat1       ,200     ,0.0001
Initial Flow Loc=CauceLat1       ,CauceLat1       ,46      ,0.0001
Boundary Location=CauceLat1       ,CauceLat1       ,200     ,        ,                ,                ,                ,                                ,                                ,
Interval=1MIN
Flow Hydrograph= 4321
       0       0       0       0       0       0       0       0       0       0
       0       0       0       0       0       0       0       0      .1      .1
      .1      .1      .1      .1      .2      .2      .2      .2      .3      .3
      .3      .4      .4      .5      .5      .6      .6      .7      .8      .8
      .9       1     1.1     1.2     1.2     1.3     1.4     1.5     1.7     1.8
     1.9       2     2.1     2.3     2.4     2.6     2.7     2.9       3     3.2
     3.4     3.5     3.7     3.9     4.1     4.3     4.5     4.7     4.9     5.1
     5.4     5.6     5.8     6.1     6.3     6.6     6.8     7.1     7.3     7.6
     7.9     8.2     8.5     8.8     9.1     9.4     9.7    10.1    10.4    10.7
    11.1    11.5    11.8    12.2    12.6      13    13.3    13.7    14.2    14.6
      15    15.4    15.9    16.3    16.8    17.2    17.7    18.2    18.7    19.2
    19.7    20.2    20.7    21.2    21.8    22.3    22.9    23.5      24    24.6
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Stage Hydrograph TW Check=0
Use DSS=False
Use Fixed Start Time=False
Is Critical Boundary=False
Boundary Location=CauceLat1       ,CauceLat1       ,46      ,        ,                ,                ,                ,                                ,                                ,
Friction Slope=0.009287
Precipitation Mode=Disable
Wind Mode=No Wind Forces
Wave Mode=No Wave Forcing
Met BC=Precipitation|Expanded View=0
Met BC=Precipitation|Point Interpolation=Nearest
Met BC=Precipitation|Gridded Source=DSS
Met BC=Precipitation|Gridded Interpolation=
Met BC=Evapotranspiration|Expanded View=0
Met BC=Evapotranspiration|Point Interpolation=Nearest
Met BC=Evapotranspiration|Gridded Source=DSS
Met BC=Evapotranspiration|Gridded Interpolation=
Met BC=Wind Speed|Expanded View=0
Met BC=Wind Speed|Point Interpolation=Nearest
Met BC=Wind Speed|Gridded Source=DSS
Met BC=Wind Speed|Gridded Interpolation=
Met BC=Wind Direction|Expanded View=0
Met BC=Wind Direction|Point Interpolation=Nearest
Met BC=Wind Direction|Gridded Source=DSS
Met BC=Wind Direction|Gridded Interpolation=
Met BC=Wind Velocity X|Expanded View=0
Met BC=Wind Velocity X|Point Interpolation=Nearest
Met BC=Wind Velocity X|Gridded Source=DSS
Met BC=Wind Velocity X|Gridded Interpolation=
Met BC=Wind Velocity Y|Expanded View=0
Met BC=Wind Velocity Y|Point Interpolation=Nearest
Met BC=Wind Velocity Y|Gridded Source=DSS
Met BC=Wind Velocity Y|Gridded Interpolation=
Met BC=Wave Forcing X|Expanded View=0
Met BC=Wave Forcing X|Point Interpolation=Nearest
Met BC=Wave Forcing X|Gridded Source=DSS
Met BC=Wave Forcing X|Gridded Interpolation=
Met BC=Wave Forcing Y|Expanded View=0
Met BC=Wave Forcing Y|Point Interpolation=Nearest
Met BC=Wave Forcing Y|Gridded Source=DSS
Met BC=Wave Forcing Y|Gridded Interpolation=
Met BC=Air Density|Mode=Constant
Met BC=Air Density|Expanded View=0
Met BC=Air Density|Constant Value=1.225
Met BC=Air Density|Constant Units=kg/m3
Met BC=Air Density|Point Interpolation=Nearest
Met BC=Air Density|Gridded Source=DSS
Met BC=Air Density|Gridded Interpolation=
Met BC=Air Temperature|Expanded View=0
Met BC=Air Temperature|Point Interpolation=Nearest
Met BC=Air Temperature|Gridded Source=DSS
Met BC=Air Temperature|Gridded Interpolation=
Met BC=Humidity|Expanded View=0
Met BC=Humidity|Point Interpolation=Nearest
Met BC=Humidity|Gridded Source=DSS
Met BC=Humidity|Gridded Interpolation=
Met BC=Air Pressure|Mode=Constant
Met BC=Air Pressure|Expanded View=0
Met BC=Air Pressure|Constant Value=1013.2
Met BC=Air Pressure|Constant Units=mb
Met BC=Air Pressure|Point Interpolation=
Met BC=Air Pressure|Gridded Source=DSS
Met BC=Air Pressure|Gridded Interpolation=
Non-Newtonian Method= 0 ,
Non-Newtonian Constant Vol Conc=0
Non-Newtonian Yield Method= 0 ,
Non-Newtonian Yield Coef=0, 0
User Yeild=   0
Non-Newtonian Sed Visc= 0 ,
Non-Newtonian Obrian B=0
User Viscosity=0
User Viscosity Ratio=0
Herschel-Bulkley Coef=0, 0
Clastic Method= 0 ,
Coulomb Phi=0
Voellmy X=0
Non-Newtonian Hindered FV= 0
Non-Newtonian FV K=0
Non-Newtonian ds=0
Non-Newtonian Max Cv=0
Non-Newtonian Bulking Method= 0 ,
Non-Newtonian High C Transport= 0 ,
Lava Activation= 0
Temperature=1300,15,,15,14,980
Heat Ballance=1,1200,0.5,1,70,0.95
Viscosity=1000,,,
Profile Coefficient=4,1.3,
Lava Param=,2500,

--- HECRAS_v0_EstructuraRapidaCauceLateral.g01 (geometry) ---

Geom Title=RapidaCauceLat1
Program Version=6.70

River Reach=CauceLat1       ,CauceLat1
Reach XY= 2
        1000200.        1000000.        1000000.        1000000.

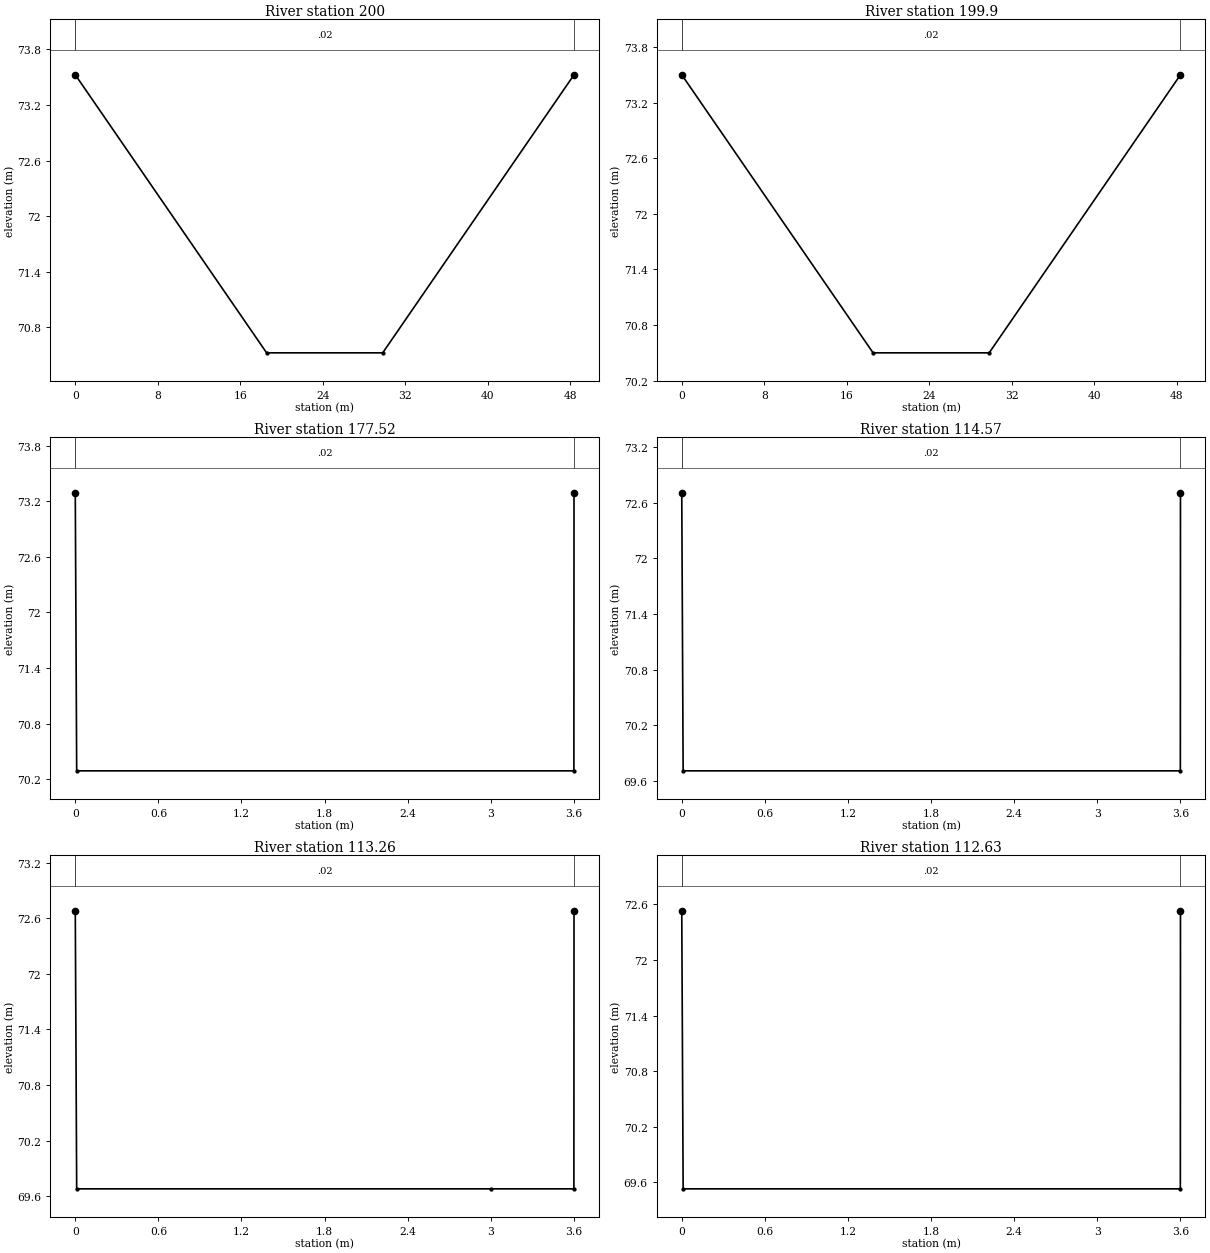
Type RM Length L Ch R = 1 ,200     ,0.1,0.1,0.1
#Sta/Elev= 4
       0  73.526  18.555  70.526  29.815  70.526  48.369  73.526
#Mann= 3 ,0,0
       0    .035       0       0     .02       0  48.369    .035       0
Bank Sta=0,48.369
XS Rating Curve= 0 ,0
Exp/Cntr=0.3,0.1

Type RM Length L Ch R = 1 ,199.9   ,22.38,22.38,22.38
BEGIN DESCRIPTION:
0.000
18.555
29.815
48.369
END DESCRIPTION:
#Sta/Elev= 4
       0    73.5  18.555    70.5  29.815    70.5  48.369    73.5
#Mann= 3 ,0,0
       0    .035       0       0     .02       0  48.369    .035       0
Bank Sta=0,48.369
XS Rating Curve= 0 ,0
Exp/Cntr=0.3,0.1

Type RM Length L Ch R = 1 ,177.52  ,0.035,0.02,0.035
#Sta/Elev= 4
       0   73.29     .01   70.29     3.6   70.29   3.601   73.29
#Mann= 3 ,0,0
       0    .035       0       0     .02       0   3.601    .035       0
Bank Sta=0,3.601
XS Rating Curve= 0 ,0
Exp/Cntr=0.3,0.1

Type RM Length L Ch R = 1 ,114.57  ,85.33,85.33,85.33
#Sta/Elev= 4
       0  72.708     .01  69.708     3.6  69.708   3.601  72.708
#Mann= 3 ,0,0
       0    .035       0       0     .02       0   3.601    .035       0
Bank Sta=0,3.601
XS Rating Curve= 0 ,0
Exp/Cntr=0.3,0.1

Type RM Length L Ch R = 1 ,113.26  ,1.31,1.31,1.31
#Sta/Elev= 5
       0   72.68     .01   69.68       3   69.68     3.6   69.68   3.601   72.68
#Mann= 3 ,0,0
       0    .035       0       0     .02       0   3.601    .035       0
Bank Sta=0,3.601
XS Rating Curve= 0 ,0
Exp/Cntr=0.3,0.1

Type RM Length L Ch R = 1 ,112.63  ,2.62,2.62,2.62
#Sta/Elev= 4
       0   72.53     .01   69.53     3.6   69.53   3.601   72.53
#Mann= 3 ,0,0
       0    .035       0       0     .02       0   3.601    .035       0
Bank Sta=0,3.601
XS Rating Curve= 0 ,0
Exp/Cntr=0.3,0.1

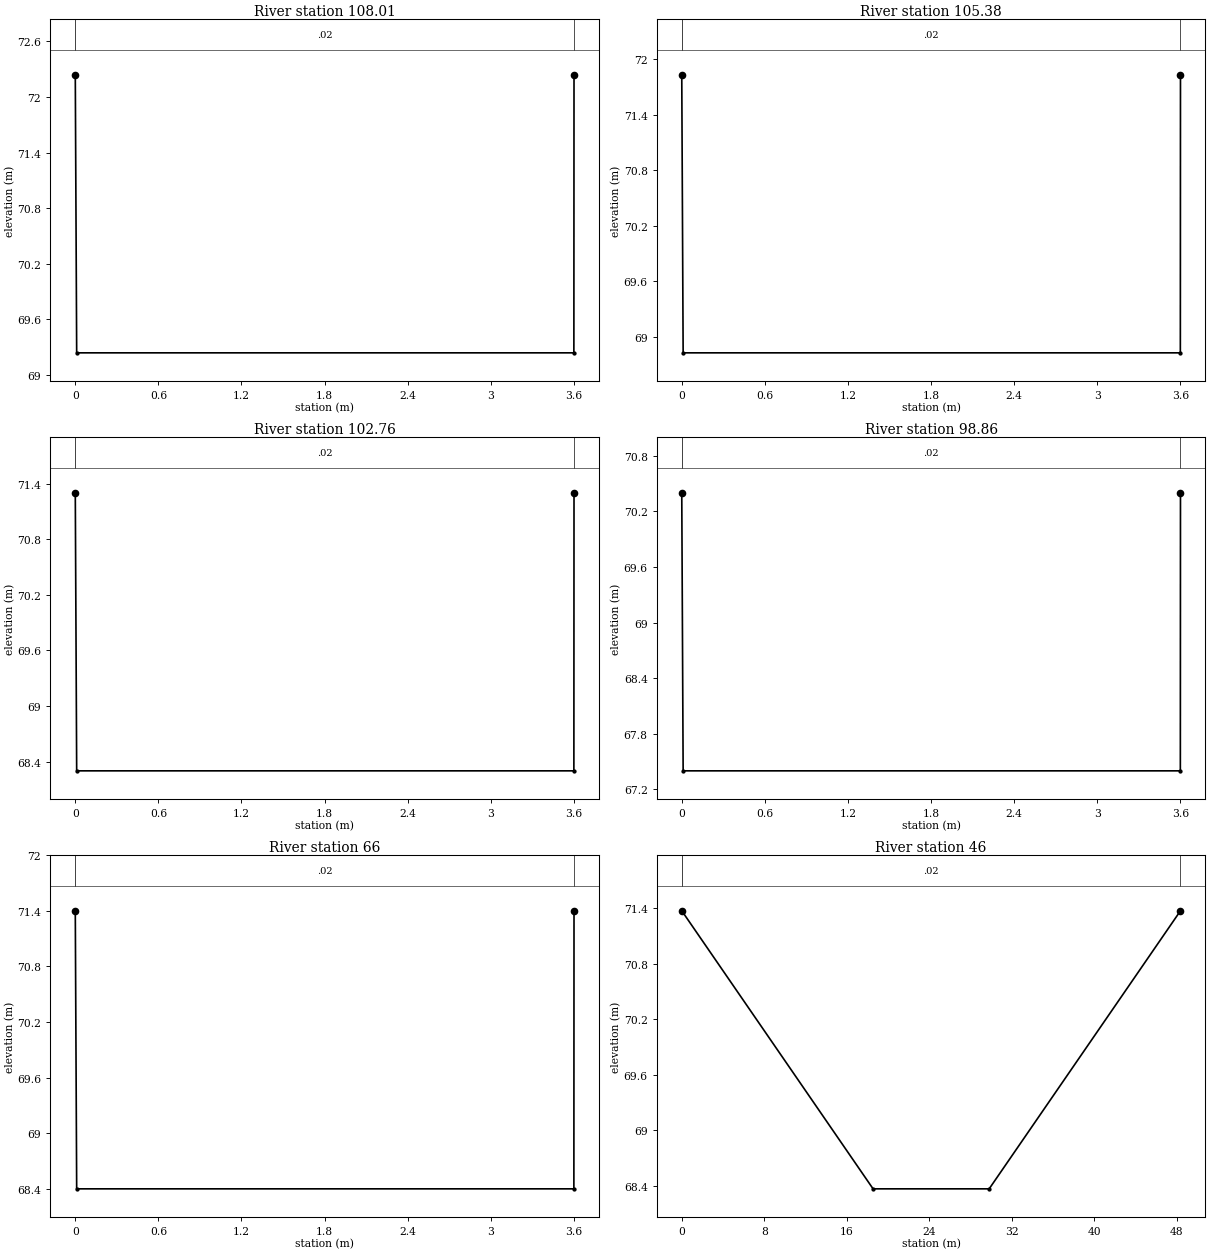
Type RM Length L Ch R = 1 ,108.01  ,2.62,2.62,2.62
#Sta/Elev= 4
       0   72.24     .01   69.24     3.6   69.24   3.601   72.24
#Mann= 3 ,0,0
       0    .035       0       0     .02       0   3.601    .035       0
Bank Sta=0,3.601
XS Rating Curve= 0 ,0
Exp/Cntr=0.3,0.1

Type RM Length L Ch R = 1 ,105.38  ,2.62,2.62,2.62
#Sta/Elev= 4
       0   71.83     .01   68.83     3.6   68.83   3.601   71.83
#Mann= 3 ,0,0
       0    .035       0       0     .02       0   3.601    .035       0
Bank Sta=0,3.601
XS Rating Curve= 0 ,0
Exp/Cntr=0.3,0.1

Type RM Length L Ch R = 1 ,102.76  ,2.62,2.62,2.62
#Sta/Elev= 4
       0    71.3     .01    68.3     3.6    68.3   3.601    71.3
#Mann= 3 ,0,0
       0    .035       0       0     .02       0   3.601    .035       0
Bank Sta=0,3.601
XS Rating Curve= 0 ,0
Exp/Cntr=0.3,0.1

Type RM Length L Ch R = 1 ,98.86   ,3.9,3.9,3.9
#Sta/Elev= 4
       0    70.4     .01    67.4     3.6    67.4   3.601    70.4
#Mann= 3 ,0,0
       0    .035       0       0     .02       0   3.601    .035       0
Bank Sta=0,3.601
XS Rating Curve= 0 ,0
Exp/Cntr=0.3,0.1

Type RM Length L Ch R = 1 ,66      ,32.8,32.8,32.8
#Sta/Elev= 4
       0    71.4     .01    68.4     3.6    68.4   3.601    71.4
#Mann= 3 ,0,0
       0    .035       0       0     .02       0   3.601    .035       0
Bank Sta=0,3.601
XS Rating Curve= 0 ,0
Exp/Cntr=0.3,0.1

Type RM Length L Ch R = 1 ,46      ,20,20,20
#Sta/Elev= 4
       0   71.37  18.555   68.37  29.815   68.37  48.369   71.37
#Mann= 3 ,0,0
       0    .035       0       0     .02       0  48.369    .035       0
Bank Sta=0,48.369
XS Rating Curve= 0 ,0
Exp/Cntr=0.3,0.1
LCMann Table=0

Chan Stop Cuts=-1
Use User Specified Reach Order=0
Composite Channel Slope=5